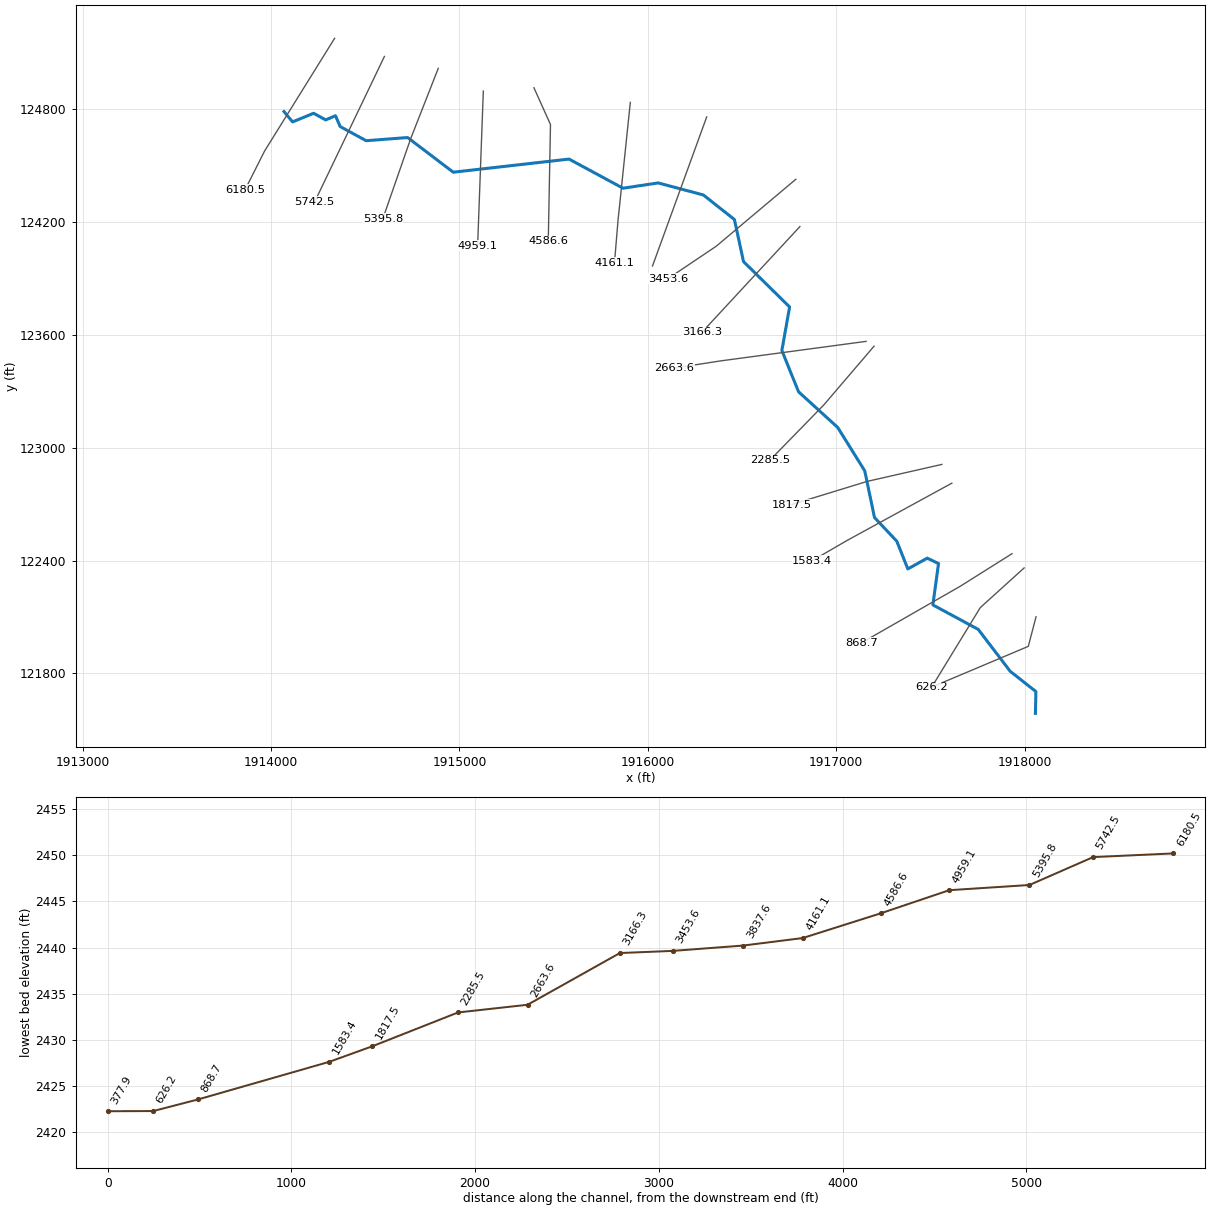
--- FssyCrk.prj (project) ---

Proj Title=FssyCrk
Current Plan=p01
Default Exp/Contr=0,0
English Units
Geom File=g01
Flow File=f01
Plan File=p01
BEGIN DESCRIPTION:
END DESCRIPTION:
DSS Export Rating Curves= 0
DSS Export Rating Curve Sorted= 0
DSS Export Volume Flow Curves= 0
DXF OffsetX= 0
DXF OffsetY= 0
DXF ScaleX= 0
DXF ScaleY= 0

--- FssyCrk.p01 (plan) ---

Plan Title=Floodplain
Program Version=4.00
Geom File=g01
Flow File=f01
K Sum by GR=0
Std Step Tol=0.01
Critical Tol=0.01
Num of Std Step Trials=20
Max Error Tol=0.3
Flow Tol Ratio=0.001
Split Flow NTrial=30
Split Flow Tol=0.02
Split Flow Ratio=0.02
Log Output Level=0
Friction Slope Method=1
Unsteady Friction Slope Method=2
Unsteady Bridges Friction Slope Method=1
Global Log Level=0
CheckData=False
Run HTab=0
Run UNet=0
Run PostProcess=0
UNET Theta=0
UNET Theta Warmup=0
UNET ZTol=0
UNET ZSATol=0
UNET MxIter=0
UNET MaxInSteps=0
UNET DtIC=0
UNET DtMin=0
UNET MaxCRTS=0
UNET WFStab=0
UNET SFStab=0
UNET WFX=0
UNET SFX=0
UNET DSS MLevel=0
UNET DZMax Abort=0
UNET Convert EG Bridges=0
UNET Use Existing IB Tables=0
UNET Froude Limit=0
UNET Froude Power=0
Write IC File=0
Echo Input=False
Echo Output=False
Write Detailed=0

--- FssyCrk.f01 (steady flow) ---

Flow Title=NFF Regression Equation
Program Version=4.00
Number of Profiles=1
Profile Names=P100yr
River Rch & RM=FssyCrk,Main      ,6180.5
390.9595
River Rch & RM=FssyCrk,Main      ,5742.5
487.9404
River Rch & RM=FssyCrk,Main      ,4959.1
496.3172
River Rch & RM=FssyCrk,Main      ,3453.6
549.9452
River Rch & RM=FssyCrk,Main      ,377.9
594.3168
Boundary for River Rch & Prof#=FssyCrk,Main      ,1
Up Type=0
Dn Type=3
Dn Slope=0.006464

--- FssyCrk.g01 (geometry) ---

Geom Title=USGS 3m DEM
Program Version=4.10

River Reach=FssyCrk         ,Main
Reach XY= 30
     1914068.957      124787.528     1914114.192      124733.058
     1914226.171      124778.631     1914289.973      124743.475
     1914342.057       124765.61     1914366.796      124708.319
     1914504.817      124632.798     1914724.869      124649.725
     1914967.036      124465.339      1915581.64      124535.142
     1915868.099      124380.194     1916054.619      124408.324
     1916294.332      124344.344     1916459.292      124213.716
     1916507.685      123989.848     1916752.213      123748.683
     1916711.164      123517.225     1916799.806      123297.288
     1917007.421      123108.058     1917150.999      122877.135
     1917202.734      122628.892     1917321.224       122502.59
     1917379.817      122355.454     1917482.682      122412.746
     1917542.578        122384.1      1917512.63      122164.048
     1917753.515       122033.84     1917922.786      121811.183
     1918059.505       121703.11      1918056.88      121587.195

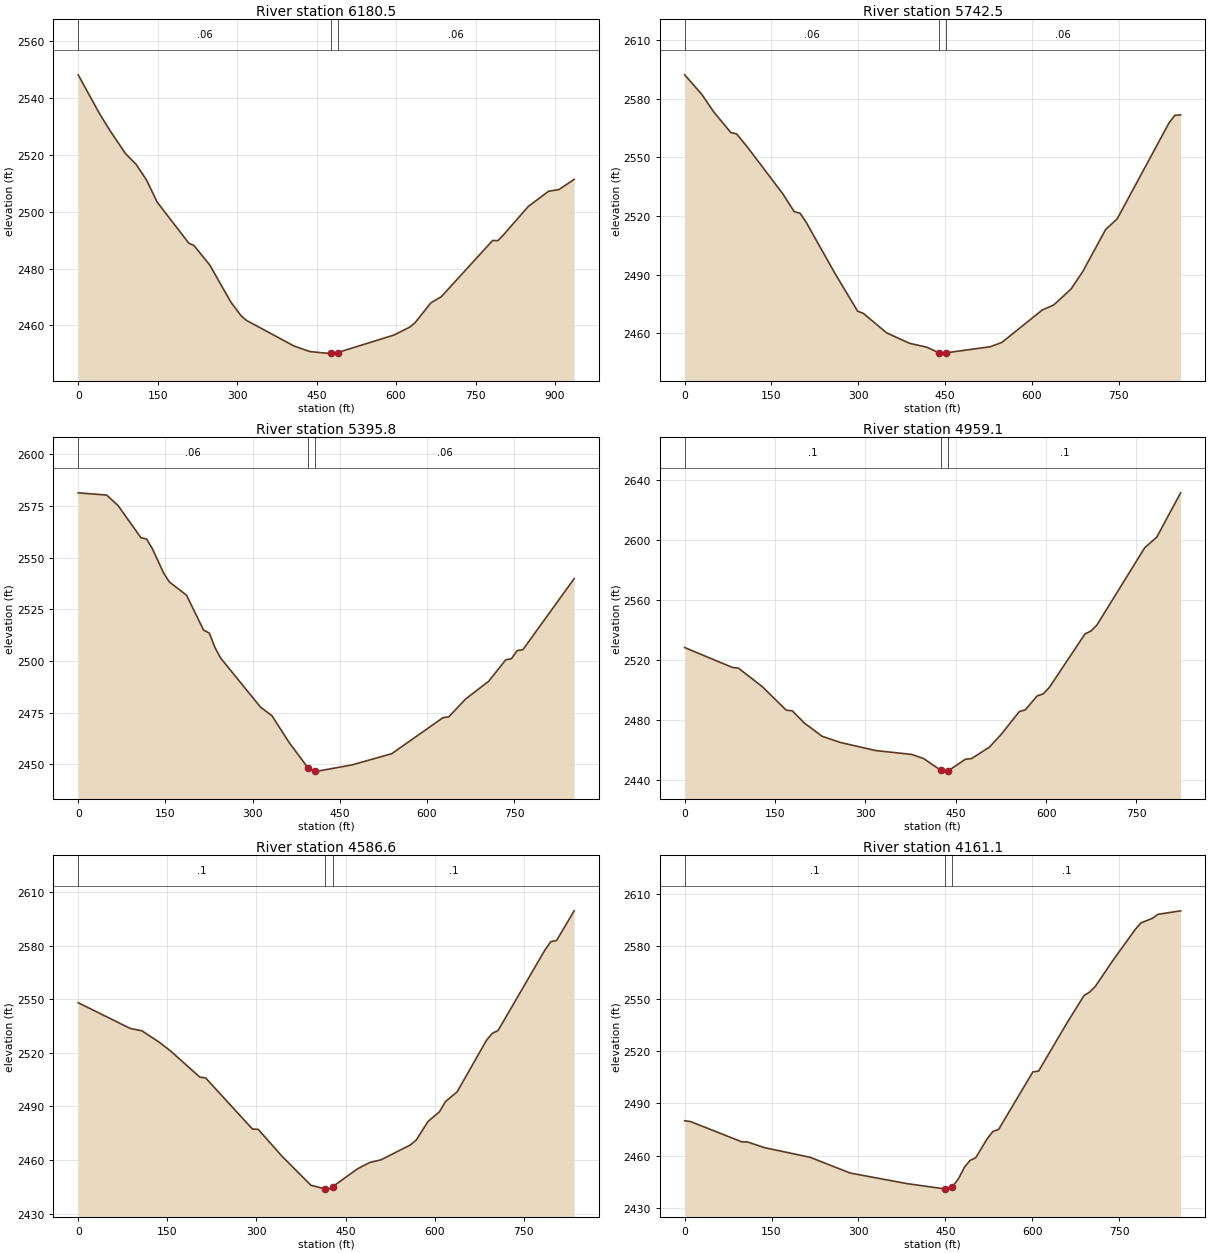
Type RM Length L Ch R = 1 ,6180.5  ,436.2,437.2,446.9
XS GIS Cut Line= 3
     1914337.308      125177.296     1913965.616       124577.68
      1913861.95      124371.596
#Sta/Elev= 30
       0 2548.24    39.8  2534.7    59.6 2528.71    89.4 2520.45   109.3 2516.73
   129.2 2511.12     149 2503.42   208.7 2488.96   218.6  2488.1   248.4 2481.22
   288.2 2468.17     308 2463.24     318  2461.7   407.4  2452.7   437.2 2450.76
     467  2450.2   477.8 2450.21   489.8 2450.41   596.2 2456.58     626 2459.38
   635.9 2460.91   665.7 2467.91   685.6 2470.11   782.4  2489.9     792  2489.8
   801.6 2491.62   849.6 2501.87   888.1 2507.25   907.3 2507.81   936.2 2511.41
#Mann= 3 , 0 , 0
       0     .06       0   477.8    .045       0   489.8     .06       0
Bank Sta=477.8,489.8
XS Rating Curve= 0 ,0
Exp/Cntr=0.3,0.1

Type RM Length L Ch R = 1 ,5742.5  ,345.2,346.7,349
XS GIS Cut Line= 2
     1914601.659      125080.843     1914231.651      124307.898
#Sta/Elev= 30
       0 2592.12    29.9 2582.01    49.8 2573.33    79.7 2562.59    89.7 2561.94
   109.6 2554.72   169.4 2531.34   189.3 2522.16   199.3 2521.35   209.2 2517.11
   259.1 2490.86   298.9 2471.24   308.9 2470.09   348.8 2460.19   388.6 2454.83
   418.5 2452.82   439.1    2450   448.4  2449.8   451.1 2449.94   528.1 2453.07
     548 2455.27   617.8 2471.84   637.7 2474.44   667.6 2482.59   687.6  2491.4
   727.4 2513.03   747.3 2518.48     837  2567.6     847 2571.42   856.9 2571.62
#Mann= 3 , 0 , 0
       0     .06       0   439.1    .045       0   451.1     .06       0
Bank Sta=439.1,451.1
XS Rating Curve= 0 ,0
Exp/Cntr=0.3,0.1

Type RM Length L Ch R = 1 ,5395.8  ,429.2,436.1,442.3
XS GIS Cut Line= 3
     1914887.548       125017.87     1914741.018      124643.406
     1914592.989      124217.006
#Sta/Elev= 30
       0 2581.35      49 2580.26    68.6  2575.2   107.9 2559.66   117.7 2559.02
   127.5 2554.41   147.1 2542.51   156.9 2538.23   186.3  2531.9   215.8 2514.95
   225.6 2513.55   235.4 2506.52   245.2 2501.43   313.8 2477.71   333.5 2473.55
   362.9 2460.68   396.1 2448.11   408.1 2446.83   411.9 2446.78   470.8 2449.76
   539.5  2455.2   627.8 2472.63   637.6 2473.03     667 2481.73   706.3 2490.21
   735.7 2500.59   745.5 2501.14   755.4 2505.07   765.2 2505.46   853.5 2539.85
#Mann= 3 , 0 , 0
       0     .06       0   396.1    .045       0   408.1     .06       0
Bank Sta=396.1,408.1
XS Rating Curve= 0 ,0
Exp/Cntr=0.3,0.1

Type RM Length L Ch R = 1 ,4959.1  ,372.4,372.6,372.7
XS GIS Cut Line= 2
     1915126.668      124896.842     1915096.432      124074.104
#Sta/Elev= 30
       0 2528.57    79.4 2515.29    89.3 2514.85     129 2502.47   168.6 2486.84
   178.6 2486.43   198.4 2478.36   228.1 2469.46   257.9 2465.38   317.4 2459.91
   376.9 2457.36   396.8 2454.58   425.6 2446.66   436.4 2446.22   437.6 2446.48
   466.2 2454.17   476.1 2454.55   505.9 2462.22   525.7 2470.84   555.5 2485.92
   565.4 2487.06   585.2 2496.35   595.2 2497.68   605.1 2501.86   664.6 2537.69
   674.5 2539.61   684.4 2543.64   763.8 2595.15   783.6 2602.08   823.3 2631.68
#Mann= 3 , 0 , 0
       0      .1       0   425.6    .045       0   437.6      .1       0
Bank Sta=425.6,437.6
XS Rating Curve= 0 ,0
Exp/Cntr=0.3,0.1

Type RM Length L Ch R = 1 ,4586.6  ,427,425.4,423.9
XS GIS Cut Line= 3
     1915395.266      124914.415      1915483.14      124718.816
     1915471.364      124098.671
#Sta/Elev= 30
       0 2548.03    87.7 2533.61   107.2 2532.32   136.5  2525.9     156 2520.87
   204.7  2506.4   214.4 2505.96   293.2 2477.36     303 2477.16   342.4 2462.33
   391.6 2445.92     416 2443.78   421.2 2443.72     428 2445.02   470.4 2455.16
   490.1 2458.55   509.8 2460.15     559 2468.43   568.9 2471.17   588.6 2481.51
   608.2 2487.09   618.1 2492.68   637.8 2498.18     687 2526.93   696.8 2530.86
   706.7  2532.5   785.5  2577.5   795.3 2582.13   805.2 2582.88   834.7 2599.44
#Mann= 3 , 0 , 0
       0      .1       0     416    .045       0     428      .1       0
Bank Sta=416,428
XS Rating Curve= 0 ,0
Exp/Cntr=0.3,0.1

Type RM Length L Ch R = 1 ,4161.1  ,328.5,323.4,318.4
XS GIS Cut Line= 3
     1915906.853      124836.672     1915841.601      124209.227
     1915822.866      123984.409
#Sta/Elev= 30
       0 2480.13     9.9  2479.7    98.6 2468.09   108.4 2468.01     138 2464.75
   216.8 2459.22   285.8 2450.24   384.4 2444.17     450 2441.13   453.4 2441.04
     462 2442.23   473.1 2447.12     483 2453.51   492.8 2457.44   502.7 2459.02
   522.4 2469.85   532.3 2474.02   542.1 2475.17   601.3 2508.08   611.1  2508.5
   660.2 2536.09   689.7 2551.76   699.5 2553.75   709.3 2557.01   738.7 2571.44
     778 2589.49   787.8 2593.23   807.4 2595.83   817.2 2598.14   856.4 2600.15
#Mann= 3 , 0 , 0
       0      .1       0     450    .045       0     462      .1       0
Bank Sta=450,462
XS Rating Curve= 0 ,0
Exp/Cntr=0.3,0.1

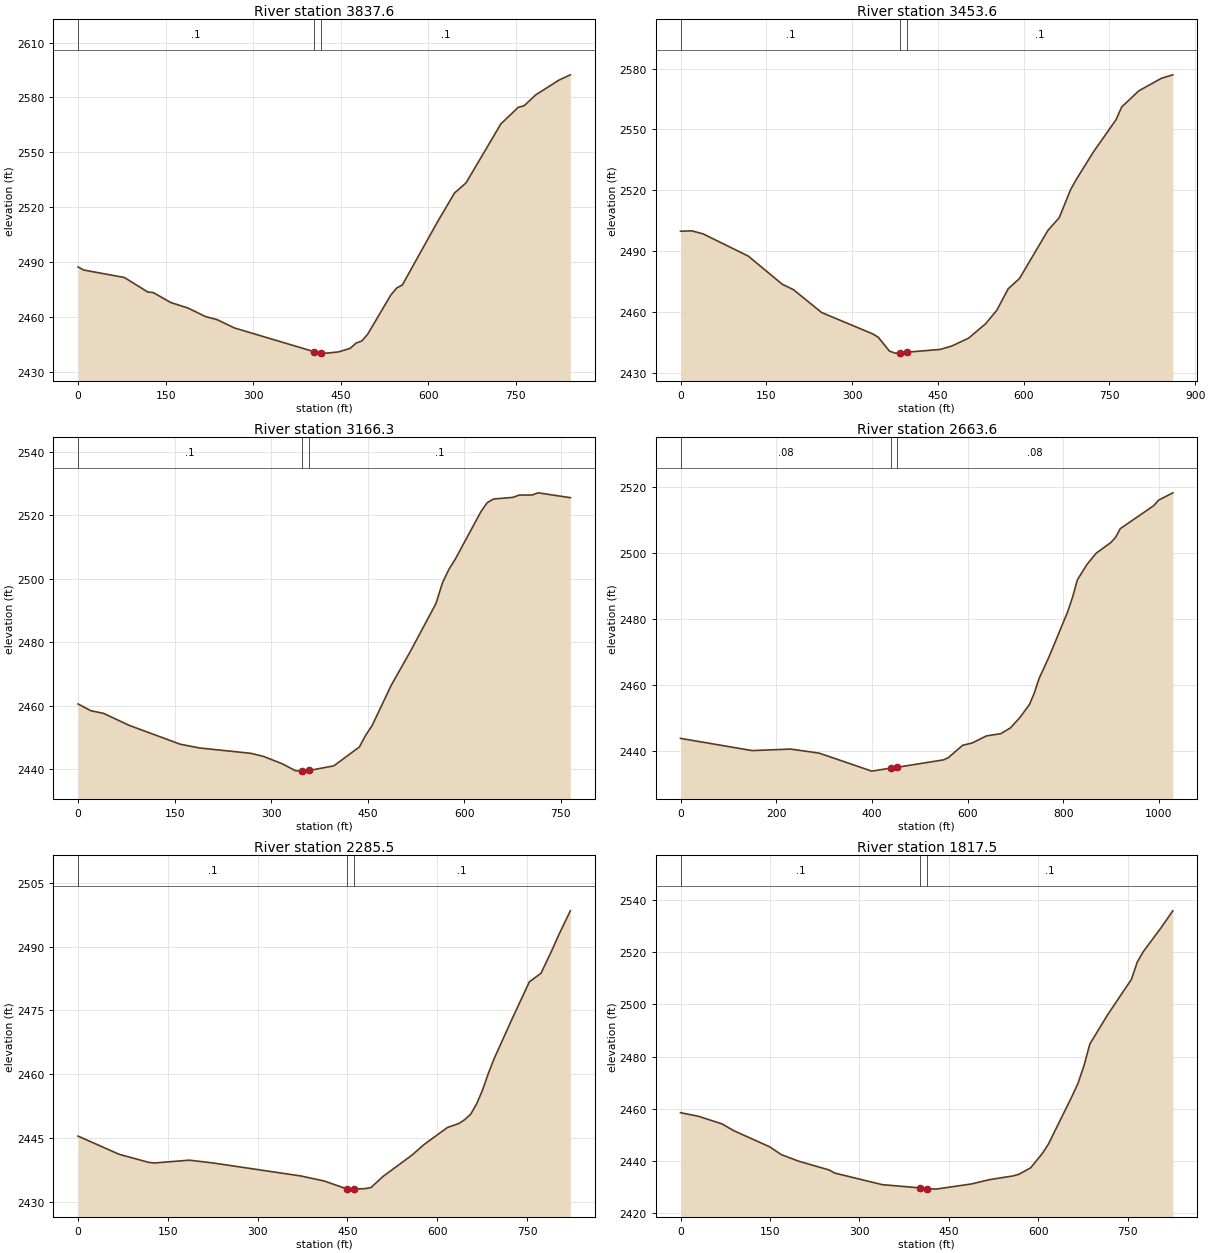
Type RM Length L Ch R = 1 ,3837.6  ,395.2,384,373
XS GIS Cut Line= 2
     1916312.243      124759.434     1916024.608      123966.673
#Sta/Elev= 30
       0  2487.3     9.9 2485.64    79.4 2481.57   119.1  2473.7     129 2473.31
   158.7 2467.91   188.5 2464.86   218.3 2460.21   238.1 2458.55   267.9 2453.99
   403.9 2441.07   415.9 2440.33   426.6 2440.23   446.5 2440.92   466.3 2442.87
   476.2  2445.7   486.2  2446.9   496.1 2450.53   535.8    2472   545.7 2475.78
   555.6  2477.5   615.1 2511.61   644.9 2527.74   664.7 2533.32   724.3  2565.5
     754 2574.56     764 2575.41   783.8 2581.32   823.5 2589.41   843.3 2592.34
#Mann= 3 , 0 , 0
       0      .1       0   403.9    .045       0   415.9      .1       0
Bank Sta=403.9,415.9
XS Rating Curve= 0 ,0
Exp/Cntr=0.3,0.1

Type RM Length L Ch R = 1 ,3453.6  ,284.8,287.4,289.8
XS GIS Cut Line= 3
     1916785.213      124427.593     1916362.222      124071.214
     1916106.925      123899.308
#Sta/Elev= 30
       0 2499.79    19.8 2499.98    39.5 2498.48   118.5 2487.53   177.8 2473.66
   197.5 2470.96   246.9 2459.67   335.8 2449.18   345.7 2447.52   365.4 2440.65
   375.3 2439.65     384 2439.76     396 2440.11   454.3 2441.49   474.1 2443.12
   503.7 2447.02   533.4  2454.1   553.1 2460.78     573 2471.38   592.8 2476.46
   642.5 2500.19   662.3 2506.47   682.2 2520.31   692.1 2525.32   721.9 2538.84
   761.6 2554.78   771.5 2561.09   801.3 2569.02     841 2575.24   860.9 2576.95
#Mann= 3 , 0 , 0
       0      .1       0     384    .045       0     396      .1       0
Bank Sta=384,396
XS Rating Curve= 0 ,0
Exp/Cntr=0.3,0.1

Type RM Length L Ch R = 1 ,3166.3  ,517.3,502.6,487.9
XS GIS Cut Line= 2
     1916806.863      124176.129     1916287.655      123614.721
#Sta/Elev= 30
       0 2460.59    19.9 2458.46    39.7 2457.62    79.4 2453.85   158.9 2447.89
   188.7 2446.72   268.1 2445.04     288 2444.07   317.8 2441.68   337.7 2439.56
   347.4 2439.42   359.4 2439.64   397.2 2441.07     437 2447.03   446.9 2450.76
   456.8 2453.78   486.6 2466.52   516.4 2477.21   556.1 2492.29   566.1 2498.78
     576 2502.97   585.9 2506.19   625.7 2521.15   635.6 2524.03   645.5 2525.17
   675.3 2525.68   685.2 2526.41   705.1 2526.43     715 2527.12   764.7 2525.59
#Mann= 3 , 0 , 0
       0      .1       0   347.4    .045       0   359.4      .1       0
Bank Sta=347.4,359.4
XS Rating Curve= 0 ,0
Exp/Cntr=0.3,0.1

Type RM Length L Ch R = 1 ,2663.6  ,363.5,378.1,392.6
XS GIS Cut Line= 3
     1917158.234      123565.645     1916385.536      123461.706
     1916139.069      123423.404
#Sta/Elev= 30
       0 2443.75   149.9 2440.05   229.9 2440.51   289.9 2439.28   399.8 2433.82
   440.6 2434.76   452.6 2434.98   549.8 2437.24   559.8  2437.9   589.7 2441.66
   609.7 2442.36   639.7 2444.51   669.7 2445.19   689.7 2446.94   709.7 2450.12
   729.7 2454.09   739.7 2457.56   749.7 2461.98   769.7 2468.26   809.6 2482.25
   819.6 2486.59   829.5  2491.8   849.5  2496.5   869.4 2499.99   899.4 2503.14
   909.4 2504.71   919.3 2507.38   989.2 2514.34   999.2    2516  1029.1 2518.24
#Mann= 3 , 0 , 0
       0     .08       0   440.6    .045       0   452.6     .08       0
Bank Sta=440.6,452.6
XS Rating Curve= 0 ,0
Exp/Cntr=0.3,0.1

Type RM Length L Ch R = 1 ,2285.5  ,480.3,468,457.3
XS GIS Cut Line= 3
     1917200.492      123540.186     1916933.592      123227.376
     1916646.693      122932.763
#Sta/Elev= 30
       0 2445.46    68.5 2441.19   117.5  2439.3   127.3 2439.14     186  2439.8
   225.2 2439.15     372 2436.09   411.2  2434.9   448.7 2433.06   450.4 2432.99
   460.7    2433   479.7 2433.11   489.5 2433.37   509.1 2435.93   558.1 2441.01
   577.6 2443.43   616.8 2447.46   636.4 2448.44   646.2 2449.36     656 2450.62
   665.8 2453.02   675.6 2456.23   685.4 2460.19   695.1 2463.67   724.5 2472.84
   753.9 2481.73   773.5 2483.77     793 2489.58   802.8  2492.7   822.4 2498.44
#Mann= 3 , 0 , 0
       0      .1       0   448.7    .045       0   460.7      .1       0
Bank Sta=448.7,460.7
XS Rating Curve= 0 ,0
Exp/Cntr=0.3,0.1

Type RM Length L Ch R = 1 ,1817.5  ,228.1,234.1,238.4
XS GIS Cut Line= 3
     1917560.553      122911.296     1917162.525      122820.592
     1916763.568      122697.885
#Sta/Elev= 30
       0 2458.58    29.9 2457.22    69.7 2454.29    89.6 2451.66   149.4 2445.54
   169.3  2442.5   199.1 2439.95   248.9 2436.68   258.9 2435.45   338.5 2431.03
   402.2 2429.78   414.2 2429.51   428.1 2429.32   487.7 2431.29   517.6 2432.92
   557.3 2434.36   567.2 2434.98   587.1 2437.46     607 2443.02   616.9 2446.52
   656.7 2464.91   666.6  2469.8   676.6 2476.55   686.5 2484.88   716.3 2496.07
   756.1 2509.58     766 2516.22   775.9 2520.17   805.8 2529.35   825.6 2535.86
#Mann= 3 , 0 , 0
       0      .1       0   402.2    .045       0   414.2      .1       0
Bank Sta=402.2,414.2
XS Rating Curve= 0 ,0
Exp/Cntr=0.3,0.1

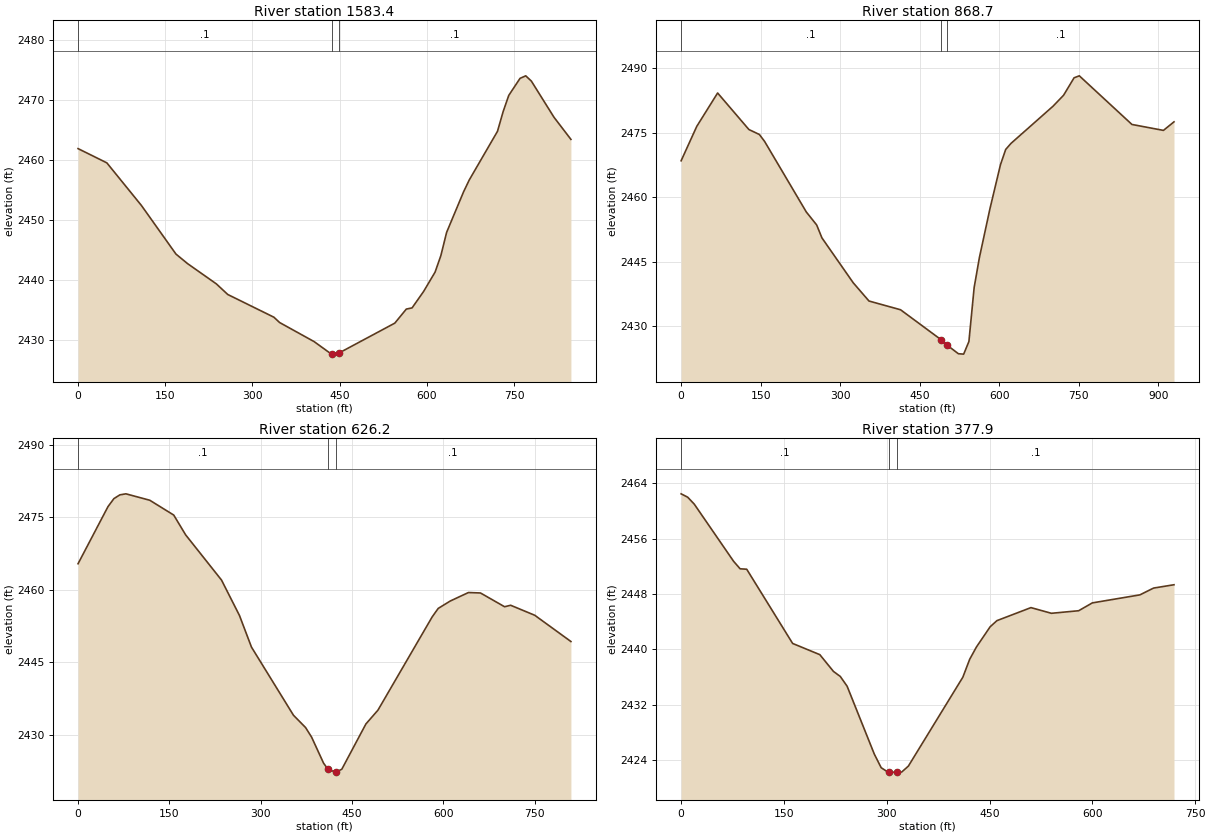
Type RM Length L Ch R = 1 ,1583.4  ,714.5,714.5,712.9
XS GIS Cut Line= 3
     1917613.212      122811.463     1917057.285      122506.853
     1916872.435      122399.439
#Sta/Elev= 30
       0 2461.86    49.5 2459.49     109 2452.39   168.4  2444.3   188.2 2442.72
   237.7 2439.35   257.5 2437.57   336.8 2433.79   346.7  2432.9   406.1 2429.72
   435.8 2427.64   436.1 2427.64   448.1 2427.79   544.8  2432.8   564.6 2435.14
   574.5 2435.34   594.3 2438.07   614.1  2441.3     624 2444.04   633.9 2447.91
   663.1 2454.67   672.8 2456.63   721.4 2464.74   731.1 2468.01   740.8 2470.72
   760.2 2473.56     770 2473.98   779.7  2473.1   818.6 2467.08   847.7  2463.4
#Mann= 3 , 0 , 0
       0      .1       0   436.1    .045       0   448.1      .1       0
Bank Sta=436.1,448.1
XS Rating Curve= 0 ,0
Exp/Cntr=0.3,0.1

Type RM Length L Ch R = 1 ,868.7   ,231.7,242.5,253.4
XS GIS Cut Line= 3
     1917932.505      122436.374      1917658.05      122263.299
     1917133.474      121962.293
#Sta/Elev= 30
       0 2468.54    29.5 2476.54    68.8  2484.3   127.8  2475.8   147.5 2474.65
   157.3 2473.05     236 2456.63   255.6  2453.6   265.5  2450.6   324.5 2440.16
   354.2 2435.92   413.7 2433.89   490.2 2426.92   502.2 2425.59   522.8 2423.66
   532.7 2423.57   542.6 2426.49   552.5 2439.06   562.4 2446.03   582.2 2457.34
   602.1 2467.62     612 2471.17   621.9 2472.57   701.2 2481.22   721.1 2483.77
   740.9 2487.83   750.8 2488.29     850 2476.98   909.4  2475.6   929.3 2477.59
#Mann= 3 , 0 , 0
       0      .1       0   490.2    .045       0   502.2      .1       0
Bank Sta=490.2,502.2
XS Rating Curve= 0 ,0
Exp/Cntr=0.3,0.1

Type RM Length L Ch R = 1 ,626.2   ,261.4,248.3,235.1
XS GIS Cut Line= 3
     1917996.965      122360.712     1917764.214      122149.641
     1917506.394      121726.815
#Sta/Elev= 30
       0 2465.43    49.1 2477.23    58.9  2478.9    68.7 2479.68    78.6 2479.89
   117.8 2478.56   157.1  2475.5   176.7  2471.4   235.6 2462.05   265.1 2454.72
   284.8 2448.18   353.8 2434.08   373.6 2431.55   383.5 2429.57   403.3 2424.15
   410.8 2422.88   422.8 2422.33   423.2 2422.32   433.1 2422.91   472.7 2432.28
   492.5 2435.14   581.6 2454.44   591.5 2456.19   611.3 2457.72   641.1 2459.47
   660.9 2459.38   700.5 2456.53   710.4 2456.84     750 2454.77   809.4 2449.34
#Mann= 3 , 0 , 0
       0      .1       0   410.8    .045       0   422.8      .1       0
Bank Sta=410.8,422.8
XS Rating Curve= 0 ,0
Exp/Cntr=0.3,0.1

Type RM Length L Ch R = 1 ,377.9   ,386.2,377.9,369.5
XS GIS Cut Line= 3
     1918060.225      122100.931     1918019.008      121943.558
     1917506.394      121726.815
#Sta/Elev= 30
       0 2462.46     9.6 2461.97    19.1 2460.98    76.6 2452.72    86.1 2451.64
    95.7 2451.58   162.7 2440.87   202.4 2439.25   222.3 2436.83   232.2 2436.11
   242.2  2434.7   281.9  2424.9   291.9 2422.94   301.8  2422.3   302.7  2422.3
   314.7  2422.3   321.7  2422.3   331.6 2423.17   411.1    2436   421.1 2438.59
     431 2440.37   450.9 2443.27   460.8 2444.16   510.5 2446.04   540.3 2445.22
   580.1 2445.59     600 2446.72   669.5 2447.88   689.4 2448.86   719.2 2449.34
#Mann= 3 , 0 , 0
       0      .1       0   302.7    .045       0   314.7      .1       0
Bank Sta=302.7,314.7
XS Rating Curve= 0 ,0
Exp/Cntr=0.3,0.1

Chan Stop Cuts=-1
Use User Specified Reach Order=0
Composite Channel Slope=5